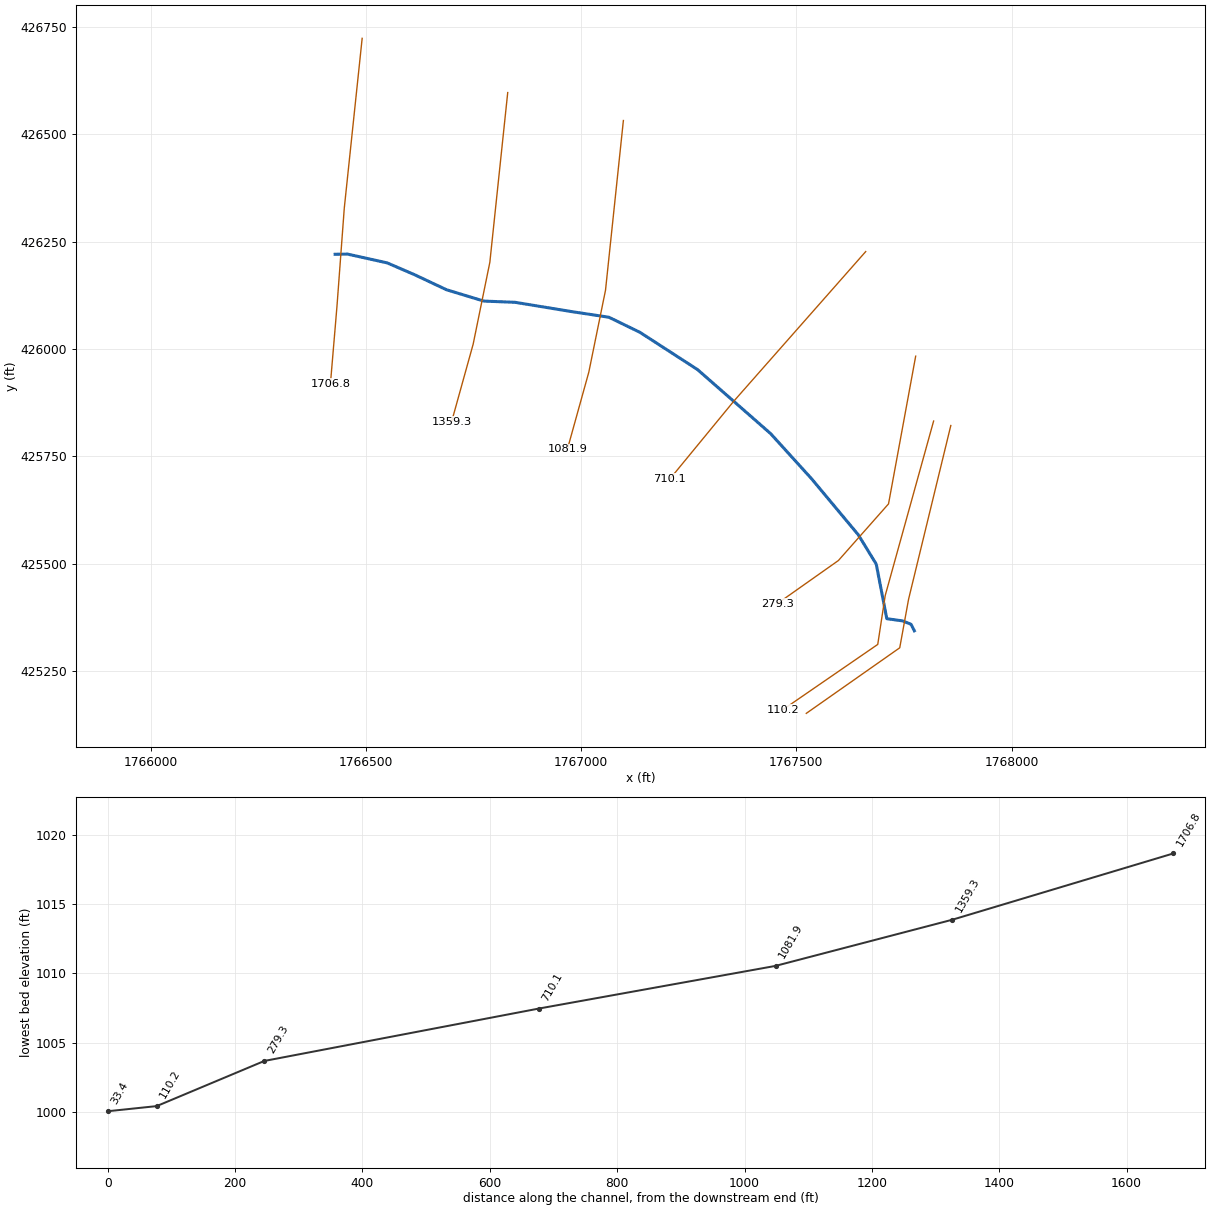
--- ShriverRun.prj (project) ---

Proj Title=ShriverRun
Current Plan=p01
Default Exp/Contr=0,0
English Units
Geom File=g01
Flow File=f01
Plan File=p01
BEGIN DESCRIPTION:
END DESCRIPTION:
DSS Export Rating Curves= 0
DSS Export Rating Curve Sorted= 0
DSS Export Volume Flow Curves= 0
DXF OffsetX= 0
DXF OffsetY= 0
DXF ScaleX= 0
DXF ScaleY= 0

--- ShriverRun.p01 (plan) ---

Plan Title=Floodplain
Program Version=4.00
Geom File=g01
Flow File=f01
K Sum by GR=0
Std Step Tol=0.01
Critical Tol=0.01
Num of Std Step Trials=20
Max Error Tol=0.3
Flow Tol Ratio=0.001
Split Flow NTrial=30
Split Flow Tol=0.02
Split Flow Ratio=0.02
Log Output Level=0
Friction Slope Method=1
Unsteady Friction Slope Method=2
Unsteady Bridges Friction Slope Method=1
Global Log Level=0
CheckData=False
Run HTab=0
Run UNet=0
Run PostProcess=0
UNET Theta=0
UNET Theta Warmup=0
UNET ZTol=0
UNET ZSATol=0
UNET MxIter=0
UNET MaxInSteps=0
UNET DtIC=0
UNET DtMin=0
UNET MaxCRTS=0
UNET WFStab=0
UNET SFStab=0
UNET WFX=0
UNET SFX=0
UNET DSS MLevel=0
UNET DZMax Abort=0
UNET Convert EG Bridges=0
UNET Use Existing IB Tables=0
UNET Froude Limit=0
UNET Froude Power=0
Write IC File=0
Echo Input=False
Echo Output=False
Write Detailed=0

--- ShriverRun.f01 (steady flow) ---

Flow Title=NFF Regression Equation
Program Version=4.10
Number of Profiles= 1
Profile Names=P100yr
River Rch & RM=ShriverRun,Main            ,1706.8
     886
River Rch & RM=ShriverRun,Main            ,279.3
     908
Boundary for River Rch & Prof#=ShriverRun,Main            , 1
Up Type= 0
Dn Type= 3
Dn Slope=0.00475
DSS Import GetInterval= 0
DSS Import GetPeak= 0
DSS Import FillOption= 0

--- ShriverRun.g01 (geometry) ---

Geom Title=USGS 10m DEM
Program Version=4.10

River Reach=ShriverRun      ,Main
Reach XY= 20
     1766428.701      426220.743     1766457.391      426221.165
     1766549.764      426200.662     1766614.599      426172.533
     1766687.466      426138.122     1766774.103      426111.729
      1766846.97       426108.86     1766975.492      426087.631
     1767064.654      426074.109     1767136.947      426038.862
     1767270.518      425952.225      1767440.35      425803.048
     1767536.053      425697.247     1767643.794      425567.705
     1767684.487      425501.092     1767686.033      425497.235
     1767710.131      425372.156     1767746.852      425366.992
     1767766.479      425359.042     1767774.165      425343.954

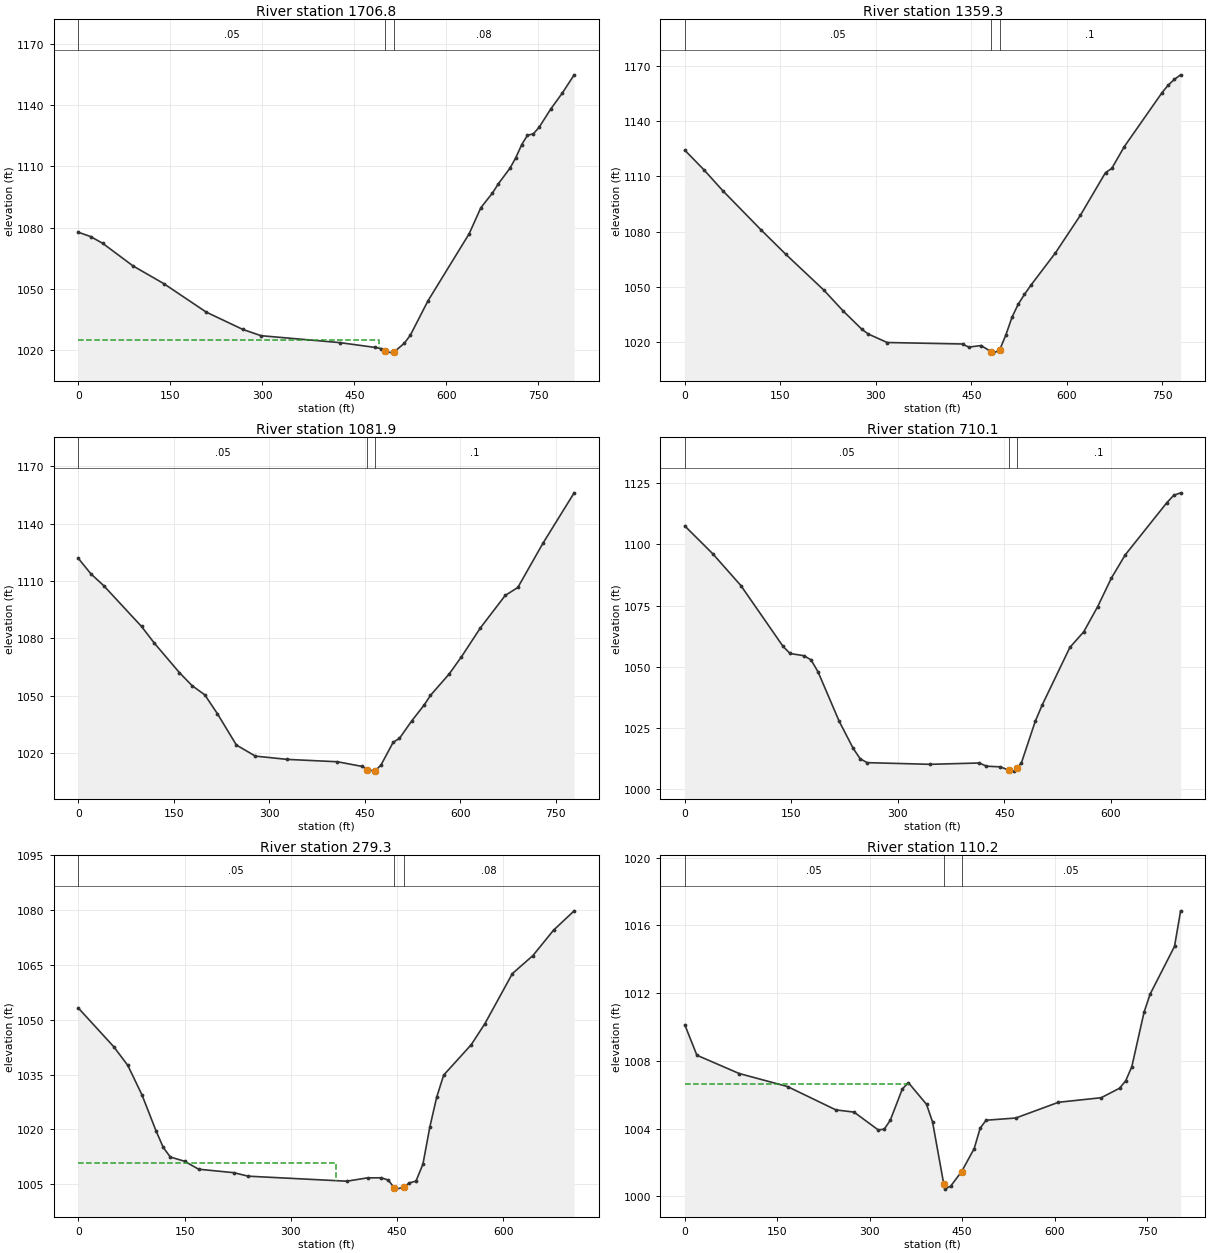
Type RM Length L Ch R = 1 ,1706.8  ,350.4,347.5,344.6
XS GIS Cut Line= 4
      1766491.51      426723.601     1766449.998      426328.437
     1766432.916      426098.601     1766417.726      425918.479
#Sta/Elev= 30
       0 1077.82    19.9  1075.7    39.7  1072.4    89.4 1061.29   139.1 1052.72
   208.6 1038.73   268.2 1030.26     298 1027.19   426.2 1023.81   483.8 1021.46
   493.4 1020.87  500.56 1019.63   512.6 1018.66  514.64 1019.13   531.8 1023.56
   541.4 1027.42   570.2 1044.26   637.3 1077.04   656.4  1089.8   675.4 1097.02
   684.9 1101.49   703.9 1109.15   713.4 1114.25     723 1120.65   732.5 1125.27
     742 1125.97   751.5  1129.2   770.5 1138.15   789.5 1146.02   808.6 1154.84
#Mann= 3 , 0 , 0
       0     .05       0  500.56    .045       0  514.64     .08       0
#XS Ineff= 2 , 0
          490.11 1025.23
Permanent Ineff=
       F       F
Bank Sta=500.56,514.64
XS Rating Curve= 0 ,0
Exp/Cntr=0.3,0.1

Type RM Length L Ch R = 1 ,1359.3  ,277.4,277.4,277.4
XS GIS Cut Line= 4
     1766829.618      426597.299     1766788.105      426202.135
     1766749.323      426011.361      1766699.41       425831.24
#Sta/Elev= 30
       0 1124.31    29.8 1113.74    59.6  1102.3   119.2 1081.15   158.9 1067.59
   218.5 1048.14   248.3 1036.99   278.1 1026.87   288.1  1024.3   317.9 1019.65
   436.3 1018.84     446 1017.14   465.5    1018   480.8 1014.74   484.9 1013.87
   494.7 1015.68   504.4 1023.81   514.1 1033.49   523.9 1040.58   533.6 1045.83
   543.4  1050.7   582.3 1068.46   621.5 1088.93   660.9 1112.12   670.7 1114.38
   690.4 1126.25   749.4 1155.48   759.2 1159.68   769.1 1162.84   778.9 1165.33
#Mann= 3 , 0 , 0
       0     .05       0   480.8    .045       0   494.7      .1       0
Bank Sta=480.8,494.7
XS Rating Curve= 0 ,0
Exp/Cntr=0.3,0.1

Type RM Length L Ch R = 1 ,1081.9  ,383.5,371.8,360.8
XS GIS Cut Line= 4
     1767098.281      426532.194     1767056.769      426137.031
     1767017.986      425946.257     1766968.073      425766.135
#Sta/Elev= 30
       0 1121.85    19.9  1113.7    39.7 1107.63    99.3 1086.22   119.2 1077.58
   158.9 1062.04   178.8 1055.24   198.7 1050.45   218.5 1040.56   248.3  1024.2
   278.1  1018.4   327.8 1016.69   407.1 1015.44     446 1012.99  453.42 1011.39
   465.5 1010.54   465.9 1010.67   475.2 1013.61   494.7 1025.69   504.4 1027.65
   523.9  1036.9   543.4 1045.19   553.1 1050.15   582.3 1061.26   601.8 1070.33
   631.4 1085.38   670.7 1102.49   690.4 1106.62   729.7 1129.67   778.9 1156.14
#Mann= 3 , 0 , 0
       0     .05       0  453.42    .045       0   465.9      .1       0
Bank Sta=453.42,465.9
XS Rating Curve= 0 ,0
Exp/Cntr=0.3,0.1

Type RM Length L Ch R = 1 ,710.1   ,430.7,430.9,430.3
XS GIS Cut Line= 3
     1767661.143      426227.001     1767354.557      425878.407
     1767206.282      425697.487
#Sta/Elev= 30
       0 1107.53    39.5 1096.14      79 1083.19   138.3  1058.4   148.2 1055.48
   167.9 1054.56   177.8 1052.87   187.7 1047.94   217.3 1027.88   237.1 1016.76
   246.9 1012.52   256.8 1010.92   345.7 1010.24   414.8 1010.78   424.7 1009.48
   444.5  1009.2   456.7 1007.77   464.2 1007.46  468.46 1008.94     474 1010.84
   493.5  1027.8   503.2 1034.42   542.2 1057.94   561.7  1064.3   581.2  1074.5
   600.7 1086.25   620.2 1095.73   678.7    1117   688.4    1120   698.2 1121.05
#Mann= 3 , 0 , 0
       0     .05       0   456.7    .045       0  468.46      .1       0
Bank Sta=456.7,468.46
XS Rating Curve= 0 ,0
Exp/Cntr=0.3,0.1

Type RM Length L Ch R = 1 ,279.3   ,133.4,169.1,207
XS GIS Cut Line= 4
     1767777.245      425983.439     1767714.171      425639.477
     1767597.775        425507.6     1767455.414      425406.905
#Sta/Elev= 30
       0 1053.21      50 1042.63    69.9  1037.5    89.9 1029.43   109.9 1019.52
   119.9 1015.09   129.9 1012.46   149.9 1011.31   169.8 1009.13   219.8 1008.17
   239.8 1007.22     379 1005.85   408.3 1006.76   427.9 1006.78   437.6 1006.15
  445.74  1004.1   447.4 1003.68   459.2 1004.13     467 1005.35   476.7 1005.88
   486.5 1010.52   496.3 1020.72     506 1028.88   515.8 1034.87   554.7 1043.18
     574 1048.94   612.8 1062.63   641.8 1067.56   670.9  1074.5     700 1079.79
#Mann= 3 , 0 , 0
       0     .05       0  445.74    .045       0   459.2     .08       0
#XS Ineff= 2 , 0
          364.46 1010.92
Permanent Ineff=
       F       F
Bank Sta=445.74,459.2
XS Rating Curve= 0 ,0
Exp/Cntr=0.3,0.1

Type RM Length L Ch R = 1 ,110.2   ,96.2,76.8,53.2
XS GIS Cut Line= 4
     1767818.912      425832.397     1767706.499      425426.147
     1767689.138      425312.215     1767468.868      425160.305
#Sta/Elev= 30
       0 1010.13    19.6 1008.33    88.2 1007.25   166.6 1006.48   245.1  1005.1
   274.5 1004.97   313.7 1003.92   323.5 1003.96   333.3 1004.49   352.9 1006.34
   362.7 1006.71   392.1 1005.43   401.9 1004.39     420 1000.73   421.5 1000.42
   431.1 1000.59   448.9 1001.45   469.5 1002.82   479.1 1004.02   488.7 1004.49
   536.8 1004.62   606.1 1005.55   675.5 1005.82   705.2 1006.38   715.2 1006.82
   725.1 1007.65   744.9 1010.86   754.8 1011.94   794.4 1014.76   804.3 1016.86
#Mann= 3 , 0 , 0
       0     .05       0     420    .045       0   448.9     .05       0
#XS Ineff= 2 , 0
          364.55 1006.63
Permanent Ineff=
       F       F
Bank Sta=420,448.9
XS Rating Curve= 0 ,0
Exp/Cntr=0.3,0.1

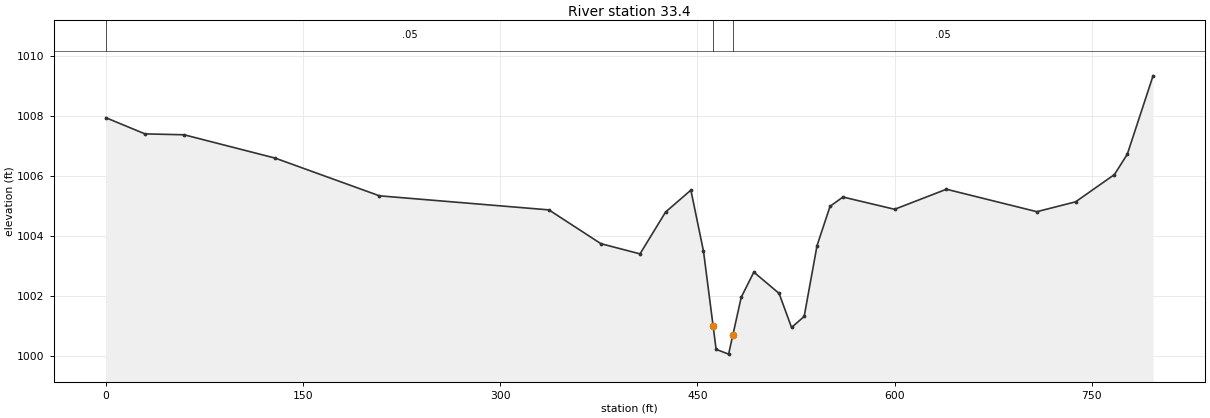
Type RM Length L Ch R = 1 ,33.4    ,54.8,33.4,11.9
XS GIS Cut Line= 4
     1767858.842       425821.98     1767760.752      425417.466
     1767740.208       425304.33     1767523.122      425151.624
#Sta/Elev= 30
       0 1007.95    29.7 1007.41    59.5 1007.38   128.8  1006.6   208.1 1005.34
     337 1004.87   376.6 1003.74   406.3  1003.4   425.8  1004.8     445 1005.53
   454.6 1003.49   461.9    1001   464.2 1000.21   473.7 1000.05   476.9 1000.68
   483.3 1001.95   492.9 1002.79   512.1 1002.08   521.6 1000.94   531.2 1001.31
     541 1003.68   550.9 1004.99   560.7  1005.3     600 1004.89   639.4 1005.56
   708.2 1004.81   737.7 1005.14   767.2 1006.05     777 1006.73   796.6 1009.35
#Mann= 3 , 0 , 0
       0     .05       0   461.9    .045       0   476.9     .05       0
#XS Ineff= 2 , 0
          444.15 1005.42
Permanent Ineff=
       F       F
Bank Sta=461.9,476.9
XS Rating Curve= 0 ,0
Exp/Cntr=0.3,0.1

Chan Stop Cuts=-1
Use User Specified Reach Order=0
Composite Channel Slope=5